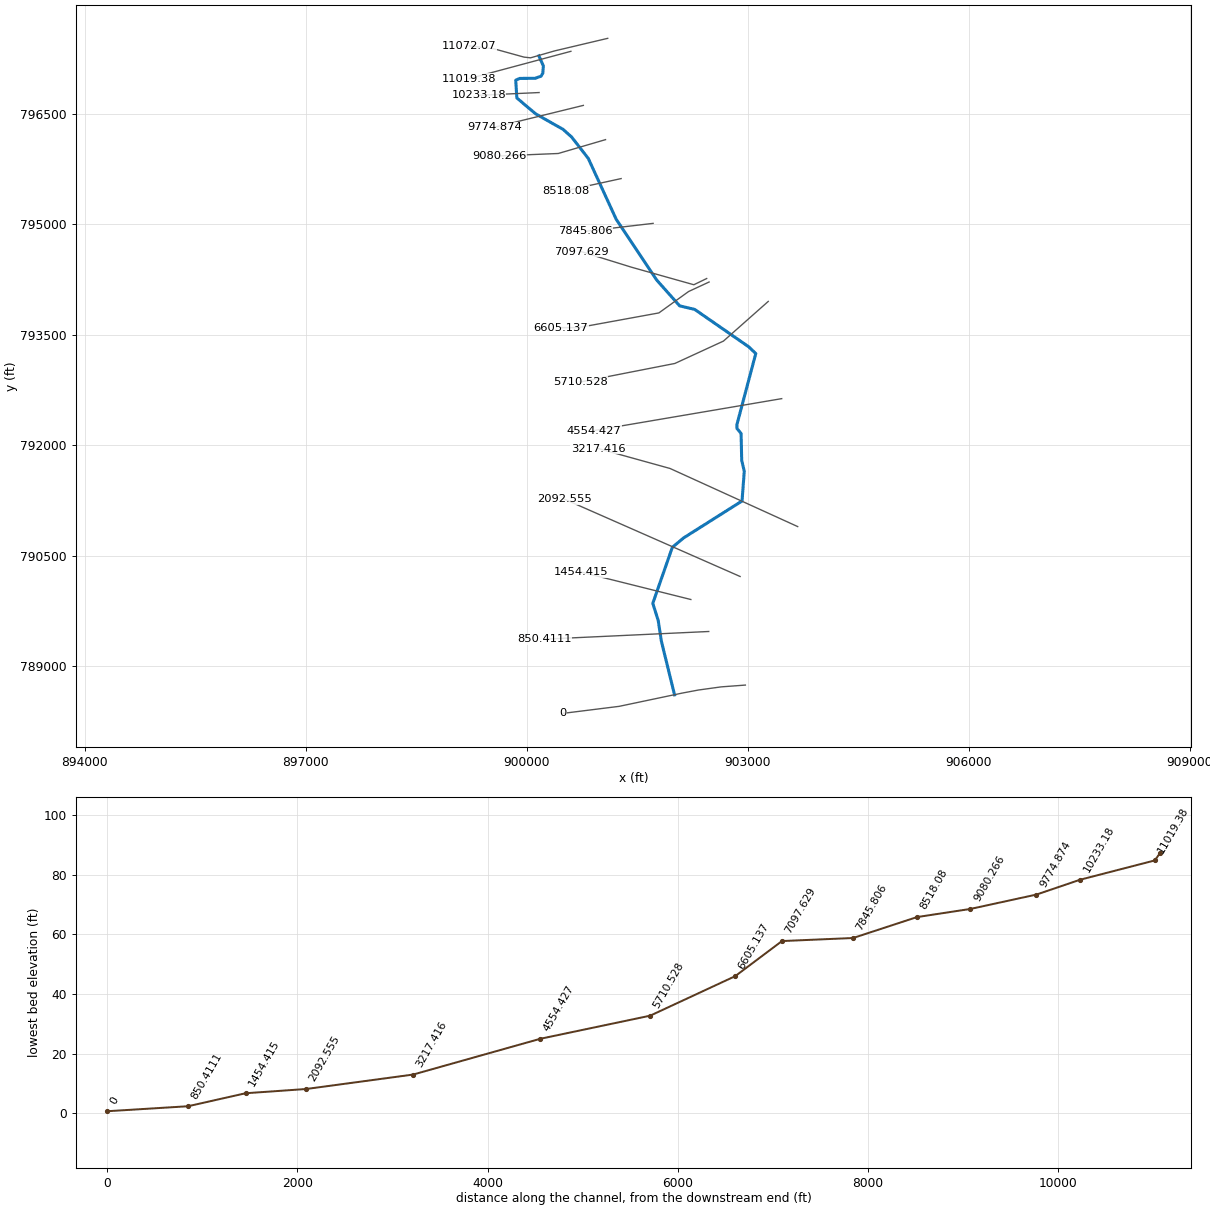
--- 11954a_ras.prj (project) ---

Proj Title=11954a
Current Plan=p01
Default Exp/Contr=0.3,0.1
English Units
Geom File=g01
Flow File=f01
Plan File=p01
Y Axis Title=Elevation
X Axis Title(PF)=Main Channel Distance
X Axis Title(XS)=Station
BEGIN DESCRIPTION:
RFD model 11954a exported to HEC-RAS
END DESCRIPTION:

--- 11954a_ras.p01 (plan) ---

Plan Title=Plan 01
Program Version=4.10
Short Identifier=Plan 01
Geom File=g01
Flow File=f01
Subcritical Flow
Calc Critical at every XS
Secant Critical Depth

--- 11954a_ras.f01 (steady flow) ---

Flow Title=Flow 01
Program Version=5.01
Number of Profiles= 6
Profile Names=10yr,25yr,50yr,100yr,100plus,500yr
River Rch & RM=11954a,16,11072.07
 3189.15 5893.97 6257.32 8140.76 9836.5112508.82
River Rch & RM=11954a,16,10233.18
 3217.93 5947.97 6314.01 8214.44 9925.5412630.79
Boundary for River Rch & Prof#=11954a,16,1
Up Type= 0
Dn Type= 2
Boundary for River Rch & Prof#=11954a,16,2
Up Type= 0
Dn Type= 2
Boundary for River Rch & Prof#=11954a,16,2
Up Type= 0
Dn Type= 2
Boundary for River Rch & Prof#=11954a,16,2
Up Type= 0
Dn Type= 2
Boundary for River Rch & Prof#=11954a,16,2
Up Type= 0
Dn Type= 2
Boundary for River Rch & Prof#=11954a,16,2
Up Type= 0
Dn Type= 2

--- 11954a_ras.g01 (geometry) ---

Geom Title=11954a
Program Version=4.10

River Reach=11954a,16
Reach XY= 30
900165.176793687797284.524854711900225.666654516797148.717322997
 900219.15623785 797049.97600356900195.284710076 797008.74336466
900114.989571186796979.446489672899905.571168405796978.361420231
899851.317696183796954.489892446 899866.14431022796712.743956283
900121.986791422 796496.82204437900492.462469937796287.521515319
900610.194212285796182.182587955900836.363085744 795890.95143583
901214.343942757795066.829239392901763.130621481794243.014221624
902075.630621481793891.451721624902279.623677036793843.708666068
903013.130621481793335.896166068903108.616732592793244.750332735
902852.540343703792281.208666068902852.540343703792229.125332735
902908.963954814 792159.68088829 902917.64451037791795.097554957
902952.366732592791647.528110512902921.984788148791243.882277179
902132.054232592790744.750332735901975.804232592790614.541999401
901711.047288148 789854.99338829 901784.83201037 789620.61838829
901828.234788148789338.500332735902006.186177036788613.673943846

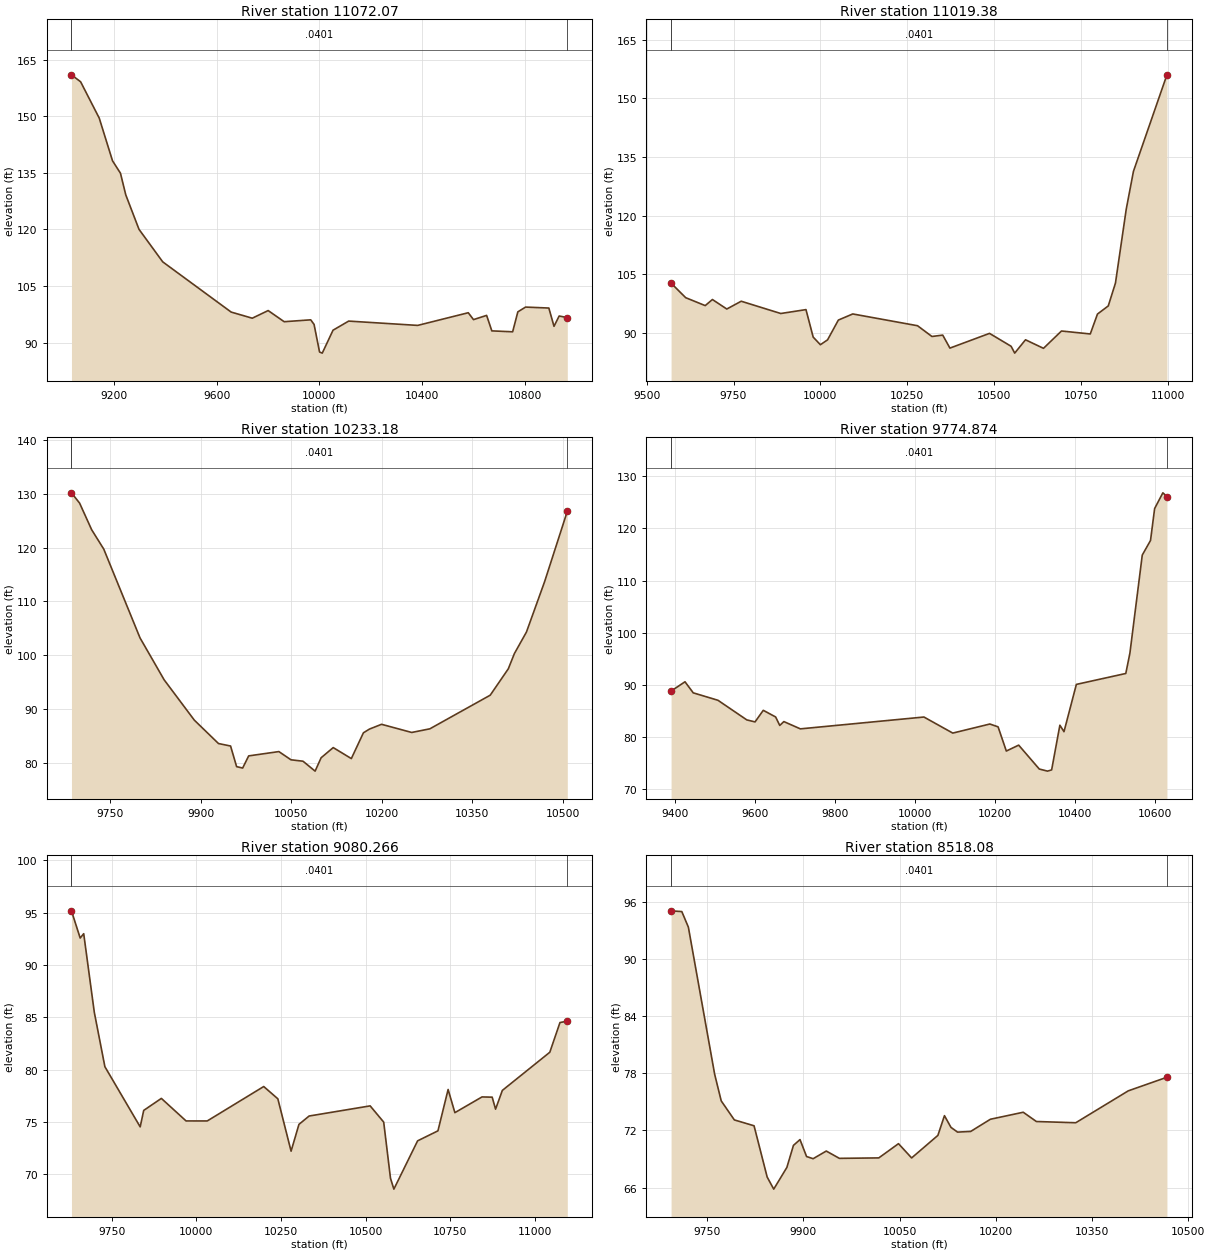
Type RM Length L Ch R = 1 ,11072.07,52.685800,52.685800,52.685800
XS GIS Cut Line= 6
901099.482127112797522.023986268900379.943693533 797351.88970307
  900052.3930279797257.653201586899963.948128572797267.108871171
899556.462911236797379.788519797 899223.35529643797419.856700259
#Sta/Elev= 30
9035.363160.95889071.049159.11199143.491149.48759195.153138.17849226.053134.8984
9246.653129.17239298.153 120.0399390.402111.42489656.69798.118699738.81896.49852
9800.66998.519489863.01195.566269966.28496.06637 9979.3294.8427510000.5887.54082
10011.1587.2464110053.0693.3191510113.95  95.73210382.4294.5892810579.1697.94501
10599.6196.1194610650.5697.2435210670.8593.1405210751.8592.8944310772.0498.17314
10802.2299.44263 10892.799.1871510912.7594.34722 10932.897.0813910964.5296.65293
#Mann= 3 , 0 , 0
9035.363  0.0401       09035.363  0.0401       010964.52  0.0401       0
#XS Ineff= 2 , 0
       0                               0
Bank Sta=9035.363,10964.52
Exp/Cntr=0.3,0.1

Type RM Length L Ch R = 1 ,11019.38,786.200700,786.200700,786.200700
XS GIS Cut Line= 2
900599.868034785797345.885902688899221.975907382796976.336289975
#Sta/Elev= 30
9570.355102.76679612.37899.049429668.57597.024949689.28298.578819730.69696.15253
9772.10998.142029885.99795.007259958.471 96.00029979.17888.980029999.88487.03399
10020.59 88.276410051.6593.3291210093.0794.8939810279.4391.8839510320.8489.13756
 10351.9 89.486510372.6186.1676110486.4989.9301310548.6286.6351310558.9784.88516
10590.0388.29179 10641.886.1119410693.5690.5372210776.3989.77922 10797.194.86324
10828.1696.9430610848.86102.782210879.92 121.68410900.63 131.33210996.94155.9787
#Mann= 3 , 0 , 0
9570.355  0.0401       09570.355  0.0401       010996.94  0.0401       0
#XS Ineff= 2 , 0
       0                               0
Bank Sta=9570.355,10996.94
Exp/Cntr=0.3,0.1

Type RM Length L Ch R = 1 ,10233.18,458.308300,458.308300,458.308300
XS GIS Cut Line= 2
900168.509761222796786.424011158899347.334815072796748.812944923
#Sta/Elev= 30
 9685.64130.19349699.164128.27269719.185123.31179739.206119.71719799.269103.2015
9839.31195.387449889.36387.879659929.40583.529859949.42683.066979959.43779.23259
9969.447 78.96659979.45881.2302310029.5182.0318510049.5380.5047810069.55 80.2385
10089.5778.3941810099.5880.88647 10119.682.7744810149.6480.7299810169.6685.52737
10179.6786.2181710199.6987.1108210249.7485.5906410279.7786.2662310379.8892.52746
10409.9197.4478710419.92100.269410439.94104.282110469.97113.633810507.68126.7628
#Mann= 3 , 0 , 0
 9685.64  0.0401       0 9685.64  0.0401       010507.68  0.0401       0
#XS Ineff= 2 , 0
       0                               0
Bank Sta=9685.64,10507.68
Exp/Cntr=0.3,0.1

Type RM Length L Ch R = 1 ,9774.874,694.607800,694.607800,694.607800
XS GIS Cut Line= 2
900768.805000597796612.065957442899565.129119187796316.426267271
#Sta/Elev= 30
9391.09788.777299425.90690.564039446.50188.439699508.28487.013899580.36583.24845
9600.95982.863179621.55385.086859652.44583.811299662.742 82.1868 9673.0482.92414
9714.22881.5274210023.1483.7997510095.2380.71649 10187.982.4572510208.4981.91381
10229.0977.2714710259.9878.4035810311.4773.8179910332.0673.4165110342.3673.65447
10362.9582.2302410373.2580.9866510404.1490.0596110527.7192.1572510538.0196.06646
 10568.9114.884510589.49117.679710599.79123.806810620.38126.827610630.55126.1177
#Mann= 3 , 0 , 0
9391.097  0.0401       09391.097  0.0401       010630.55  0.0401       0
#XS Ineff= 2 , 0
       0                               0
Bank Sta=9391.097,10630.55
Exp/Cntr=0.3,0.1

Type RM Length L Ch R = 1 ,9080.266,562.185700,562.185700,562.185700
XS GIS Cut Line= 3
 901069.72397095796147.489301459900428.442758459795959.425498814
899633.352405523795926.486576803
#Sta/Elev= 30
9631.14995.167689656.91592.568879667.33692.982599698.59985.478789729.86380.27753
9834.074 74.53039844.49576.102199896.60177.250029969.549 75.096810032.0875.09557
10198.8178.38323 10240.577.2121410279.6372.2100610302.88 74.770310332.9175.56596
10513.0676.53536 10553.174.9846810573.1269.6230610583.1268.5831810653.1873.19447
10713.2474.1507710743.2678.1008910763.2875.8881510843.3577.3906910873.37 77.3676
10883.3876.21979 10903.478.0133611043.5281.6575311073.5484.4963311095.2184.62802
#Mann= 3 , 0 , 0
9631.149  0.0401       09631.149  0.0401       011095.21  0.0401       0
#XS Ineff= 2 , 0
       0                 10530.6       0
Bank Sta=9631.149,11095.21
Exp/Cntr=0.3,0.1

Type RM Length L Ch R = 1 , 8518.08,672.274600,672.274600,672.274600
XS GIS Cut Line= 2
901281.359788147795618.882277179900526.151454814795453.951721623
#Sta/Elev= 30
9693.80295.026099710.547 94.94699720.78393.309829761.72677.897019771.96175.10195
9792.43373.10582 9823.1472.490849843.61167.113369853.84765.849149874.318 68.1248
9884.55470.43442 9894.7971.042379905.025 69.26649915.26169.039539935.73269.84089
9956.20469.0744910017.6269.1228510048.3370.61457 10068.869.1187810109.7471.48188
10119.9773.5506310130.2172.3167210140.4571.8267310160.9271.8986210191.62 73.1748
 10242.8 73.909510263.2772.9377910324.6972.8084510406.5776.1543810466.8177.57873
#Mann= 3 , 0 , 0
9693.802  0.0401       09693.802  0.0401       010466.81  0.0401       0
#XS Ineff= 2 , 0
       0                               0
Bank Sta=9693.802,10466.81
Exp/Cntr=0.3,0.1

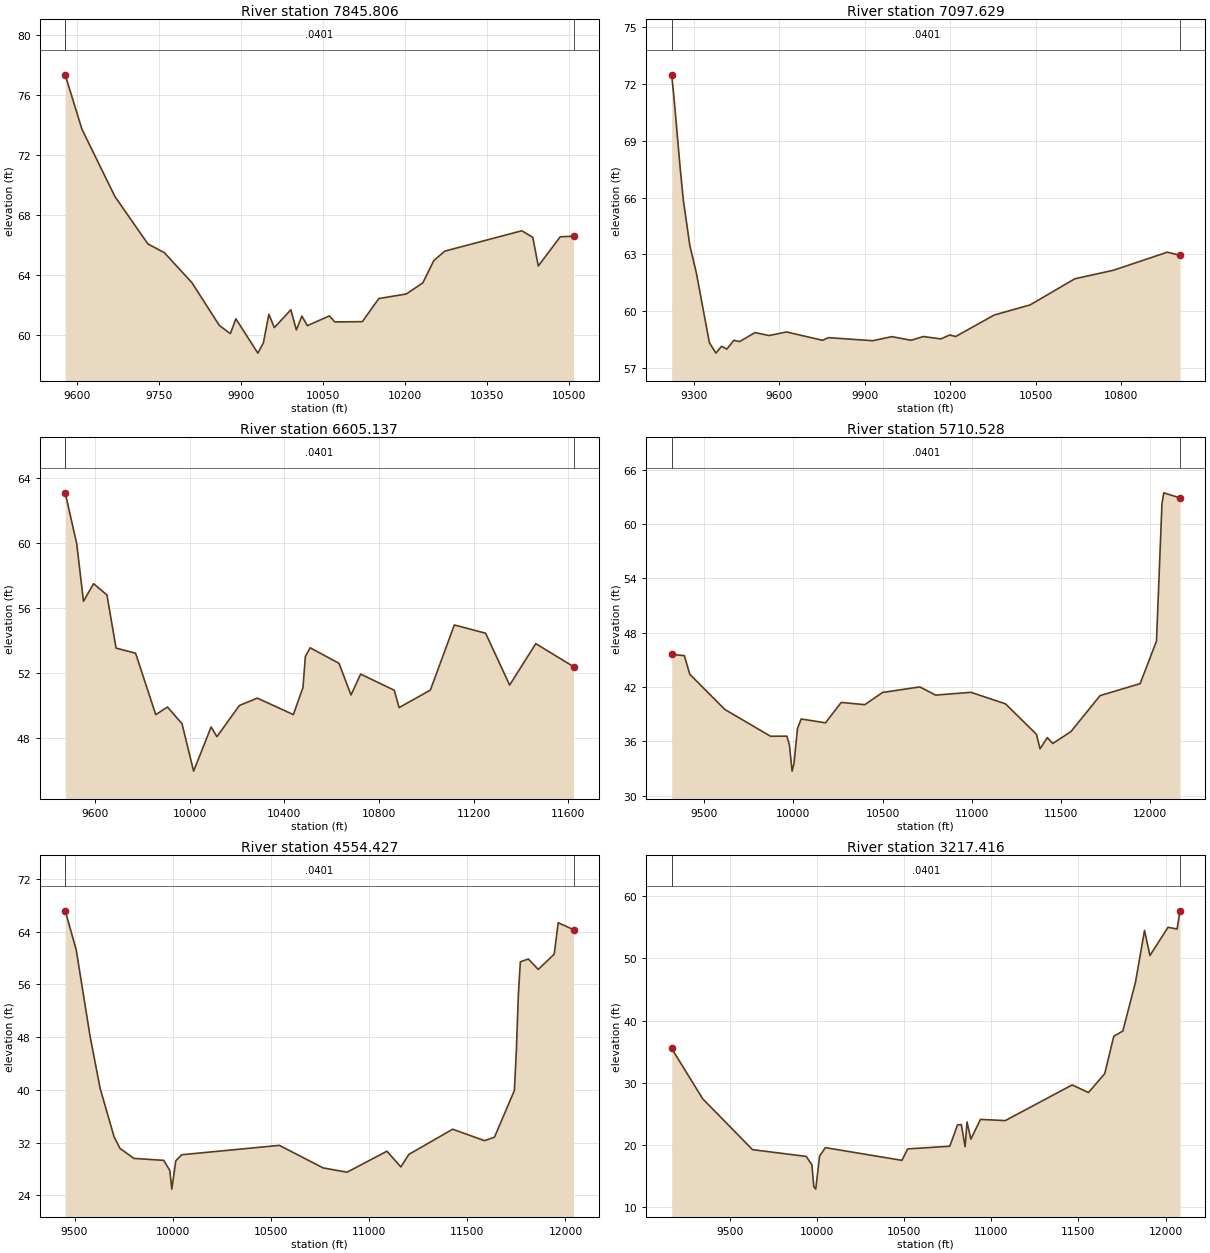
Type RM Length L Ch R = 1 ,7845.806,748.176100,748.176100,748.176100
XS GIS Cut Line= 2
901715.387565925 795011.24338829900790.908399258794902.736443846
#Sta/Elev= 30
9577.822 77.36749608.41873.74594 9668.8369.256859729.24266.097329759.448 65.5108
9809.79163.516769860.13460.660149880.27160.11466 9890.3461.105279930.61458.81618
9940.68359.495249950.75261.40268 9960.8260.518879991.02661.7058610001.0960.35798
10011.1661.2874710021.2360.6476210061.5161.2962110071.5860.8949110121.9260.91467
10152.1262.4533910202.4762.7595910232.6763.4990410252.8164.9879410272.9565.61527
10413.91 66.973110434.0566.5344810444.1264.6246410484.3966.5732110508.6566.60783
#Mann= 3 , 0 , 0
9577.822  0.0401       09577.822  0.0401       010508.65  0.0401       0
#XS Ineff= 2 , 0
       0                               0
Bank Sta=9577.822,10508.65
Exp/Cntr=0.3,0.1

Type RM Length L Ch R = 1 ,7097.629,492.492500,492.492500,492.492500
XS GIS Cut Line= 4
902442.336818172 794262.78627662902268.120572179794178.317793714
901423.435743119794415.885401887900742.408599689794627.056609152
#Sta/Elev= 30
9222.02272.474839230.17571.271739252.40267.47092 9262.7965.890859285.74263.46925
9308.63362.025529354.47658.340089377.39757.791299396.87658.148839415.63558.00369
9440.31658.467679460.42958.399139514.18658.874079564.30958.719699624.99158.90898
9751.29258.468559772.73158.607899927.88858.446459994.34258.6607210062.93 58.4689
10105.1558.6675810166.8158.5413810197.9858.7493310218.7558.6684510354.2759.80337
10479.9160.3336710636.9561.7136910773.0662.1665110961.5263.1170411006.11 62.9521
#Mann= 3 , 0 , 0
9222.022  0.0401       09222.022  0.0401       011006.11  0.0401       0
#XS Ineff= 2 , 0
       0                               0
Bank Sta=9222.022,11006.11
Exp/Cntr=0.3,0.1

Type RM Length L Ch R = 1 ,6605.137,894.609000,894.609000,894.609000
XS GIS Cut Line= 5
902475.110088738794215.481422186 902197.10554135794086.552552818
901793.512565925793795.965610512900699.762565925793596.312832735
900465.387565925793596.312832735
#Sta/Elev= 30
9472.99763.083079521.67959.95963 9550.2856.418939592.98557.499969649.48856.81097
9688.05953.543569770.74153.225259855.97249.451439905.26149.921159966.87348.90277
10016.1645.98238 10090.148.6967810114.74 48.101710209.9650.0188210285.4250.46821
 10437.949.4565610478.5651.1152310488.7253.0309110509.05 53.560910631.0452.60721
10681.8650.6598810722.5251.9434910864.8450.9528610885.1749.8861511017.3150.95959
11118.9754.9641211251.1254.4560811352.7751.2715511463.3553.8154911622.9652.40256
#Mann= 3 , 0 , 0
9472.997  0.0401       09472.997  0.0401       011622.96  0.0401       0
#XS Ineff= 2 , 0
       0                10505.88       0
Bank Sta=9472.997,11622.96
Exp/Cntr=0.3,0.1

Type RM Length L Ch R = 1 ,5710.528,1156.100500,1156.100500,1156.100500
XS GIS Cut Line= 4
903277.887565925793952.215610512902670.248677036793414.021166068
902010.526454814793110.201721623900725.804232592792858.465610512
#Sta/Elev= 30
9318.97445.589969390.18645.46012 9420.3543.401369616.41839.518769872.815  36.557
9964.03936.56869 9978.3935.615129993.47232.7066510004.1133.5608210023.6437.40088
10044.1938.46299 10180.538.0395810268.5840.2911610400.6940.0437210499.78 41.3891
10708.9642.0061110797.0341.0988810995.1141.4089811188.7240.1361211361.9636.77679
11382.3435.17094 11423.136.4065111453.6735.7566211555.5737.0780311718.6141.04579
 11942.842.3651912034.5147.0689812065.0862.2051212075.2763.4312912166.1662.86649
#Mann= 3 , 0 , 0
9318.974  0.0401       09318.974  0.0401       012166.16  0.0401       0
#XS Ineff= 2 , 0
       0                10798.12       0
Bank Sta=9318.974,12166.16
Exp/Cntr=0.3,0.1

Type RM Length L Ch R = 1 ,4554.427,1337.011200,1337.011200,1337.011200
XS GIS Cut Line= 2
903460.179232592792632.771166068900908.095899259 792198.74338829
#Sta/Elev= 30
9452.65567.166749508.62661.275939579.63148.082439630.34940.250779701.35432.89945
9731.78531.11525 9802.7929.598489954.94429.302699985.37527.760249995.51824.93795
10015.8129.2370510046.2430.1568510543.2731.5786110766.4328.1552910888.1527.50749
11091.03 30.689511162.0328.30729 11202.630.2050111425.7634.0285711588.0632.29586
11638.7832.8222211740.2139.9144911750.36 46.1059 11760.554.5192511770.6559.43079
11811.2259.8568111861.9458.2753311943.0960.6003311963.3765.3629312041.3864.31091
#Mann= 3 , 0 , 0
9452.655  0.0401       09452.655  0.0401       012041.38  0.0401       0
#XS Ineff= 2 , 0
       0                10294.72       0
Bank Sta=9452.655,12041.38
Exp/Cntr=0.3,0.1

Type RM Length L Ch R = 1 ,3217.416,1124.861700,1124.861700,1124.861700
XS GIS Cut Line= 3
903677.193121481790896.660054957901945.164499445791685.171139697
900968.859788147791955.687832735
#Sta/Elev= 30
9166.71335.529989344.92327.434499630.59819.266679938.24818.179389971.21116.83541
9982.19913.307919993.18612.9212510015.1618.2136710048.1219.5906510487.6217.54767
10520.5919.3864510762.3119.8139210806.2623.2429410828.2423.2973210850.2119.75172
 10861.223.7270810883.1720.9666810938.1124.1277411080.3323.9349611464.2729.67423
11557.6628.4446211651.0531.4842511702.9437.4939611754.8238.3338911827.4646.17735
11879.3454.5096511910.4750.4768212014.2455.0117812066.1254.7347312082.8757.65799
#Mann= 3 , 0 , 0
9166.713  0.0401       09166.713  0.0401       012082.87  0.0401       0
#XS Ineff= 2 , 0
       0                10371.29       0
Bank Sta=9166.713,12082.87
Exp/Cntr=0.3,0.1

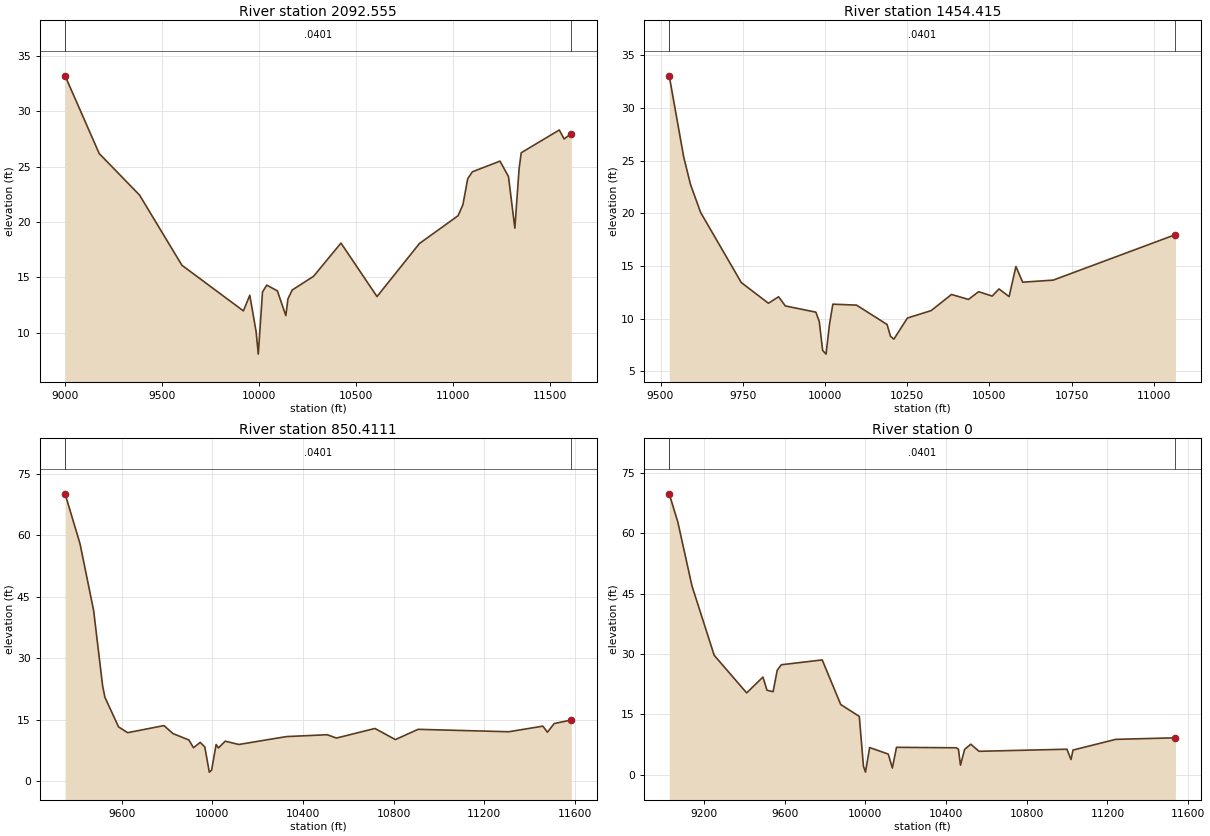
Type RM Length L Ch R = 1 ,2092.555,638.139200,638.139200,638.139200
XS GIS Cut Line= 2
902895.943121481790219.576721623900508.790343703791269.923943846
#Sta/Elev= 30
 9002.6333.186549178.46326.169159386.042 22.42929604.54616.090079921.37711.97246
9954.15213.385189986.92810.076129997.8538.070861 10019.713.6829710041.5514.29818
10096.1813.7815810139.8811.5486810150.8113.0608110172.6613.8568710282.4315.08973
10423.9418.0932210609.6613.2665510828.17 18.051911027.3320.5638411052.1621.55262
11076.99 23.9033 11101.324.5297611243.3325.4889711287.03 24.0887 11319.819.43872
11341.6524.7887611352.5826.2430211548.7628.2988411573.5927.4867311610.6427.97436
#Mann= 3 , 0 , 0
 9002.63  0.0401       0 9002.63  0.0401       011610.64  0.0401       0
#XS Ineff= 2 , 0
       0                 10148.3       0
Bank Sta=9002.63,11610.64
Exp/Cntr=0.3,0.1

Type RM Length L Ch R = 1 ,1454.415,604.004200,604.004200,604.004200
XS GIS Cut Line= 2
902227.540343703789907.076721623900734.484788147790280.340610512
#Sta/Elev= 30
9526.49733.034039570.34625.360069590.96222.753719621.88520.080669745.57813.42897
 9828.0411.465349858.96412.078279879.57911.208849972.34910.617639982.6579.731656
9992.9656.99071310003.276.63825710013.589.43138710023.8911.3771110096.0411.28538
10188.81 9.4505210199.128.34031410209.438.05507310250.6610.0613710322.8110.76574
10384.6612.29701 10436.211.8261510467.1212.5610210508.3512.1419410528.9712.81977
10559.89 12.096810580.5114.9487510601.1213.4629710693.8913.65677 11065.517.97264
#Mann= 3 , 0 , 0
9526.497  0.0401       09526.497  0.0401       0 11065.5  0.0401       0
#XS Ineff= 2 , 0
       0                10436.86       0
Bank Sta=9526.497,11065.5
Exp/Cntr=0.3,0.1

Type RM Length L Ch R = 1 ,850.4111,850.411100,850.411100,850.411100
XS GIS Cut Line= 2
902470.595899259789473.048943846900239.693121481789368.882277179
#Sta/Elev= 30
9350.52970.115669416.19657.987699476.26241.722229516.30523.227499526.31620.51013
9586.381 13.30689626.42511.894419786.59913.625459826.64311.667329896.71910.12116
9916.7418.2294819946.7749.5270719966.7958.4223189986.817 2.280749996.8282.745266
10016.859.01414310026.868.17071310056.899.82614810116.969.02053710327.1910.94458
10507.3811.3964410547.4310.5855910717.6112.9226310807.71 10.211110907.8212.71285
11308.2612.1243311458.4213.4881111478.4412.0155511508.4714.1220211583.86 14.9876
#Mann= 3 , 0 , 0
9350.529  0.0401       09350.529  0.0401       011583.86  0.0401       0
#XS Ineff= 2 , 0
       0                10845.51       0
Bank Sta=9350.529,11583.86
Exp/Cntr=0.3,0.1

Type RM Length L Ch R = 1 ,       0,0.000000,0.000000,0.000000
XS GIS Cut Line= 6
902967.368251764788745.902398818902640.514537252788721.711977817
902330.533118172788678.836435111902109.656687633788637.191572726
901254.349824616788457.298825777900491.429232592788361.937832735
#Sta/Elev= 30
9028.34969.819099070.79462.836369140.92146.936799251.19729.653719412.07520.30316
9492.68124.247119512.83220.958129543.17320.614589563.40925.918789583.64527.30362
9786.50328.510149878.24617.413869970.28514.455139990.7522.06272110000.990.599029
10021.476.71123710113.655.09346110134.131.62785110154.616.77037410451.196.653202
 10461.46.30377210471.622.33051610492.056.24093610522.717.55154710563.485.778198
10999.086.29845811019.243.73215811029.316.08974911240.95 8.74781 11536.89.134075
#Mann= 3 , 0 , 0
9028.349  0.0401       09028.349  0.0401       0 11536.8  0.0401       0
#XS Ineff= 2 , 0
       0                10939.44       0
Bank Sta=9028.349,11536.8
Exp/Cntr=0.3,0.1